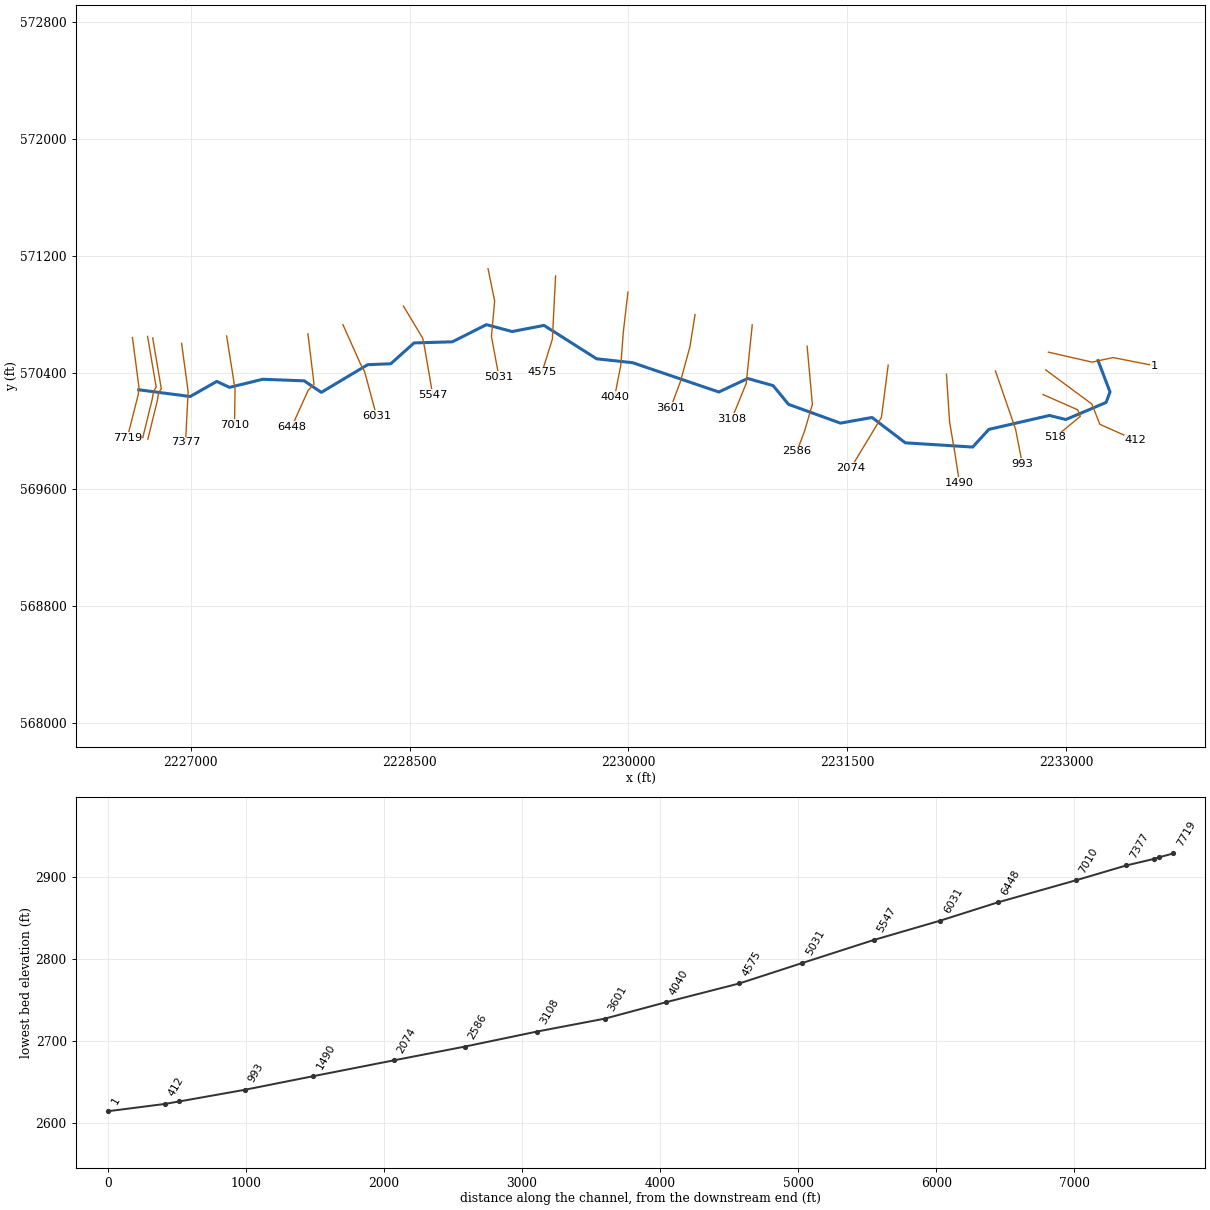
--- SNAKERN.prj (project) ---

Proj Title=SNAKERN
Current Plan=p01
Default Exp/Contr=0,0
English Units
Geom File=g01
Flow File=f01
Plan File=p01
BEGIN DESCRIPTION:
----------MODEL BY WOOD PLC 2022----------
AFH study
Randolph County, WV
HEC-RAS Version: RAS 6.2
Vertical Datum: NAVD88
Projection: NAD 1983 StatePlane West Virginia S FIPS 4702 (US Feet)
Terrain: 1-meter LIDAR (FEMA Region III 3DEP collected 2016-2018)
Land Use: 2019 NLCD
Hydrologic Method:
WV SIR2010-5033 regression equations
Additional Model Notes:
Coincident peak with ELKWTRFK; 2 shared XSs to tie-in
END DESCRIPTION:
DSS Export Rating Curves= 0
DSS Export Rating Curve Sorted= 0
DSS Export Volume Flow Curves= 0
DXF OffsetX= 0
DXF OffsetY= 0
DXF ScaleX= 0
DXF ScaleY= 0

--- SNAKERN.p01 (plan) ---

Plan Title=Floodplain
Program Version=6.20
Short Identifier=Floodplain
Geom File=g01
Flow File=f01
Subcritical Flow
K Sum by GR= 0
Std Step Tol= 0.01
Critical Tol= 0.01
Num of Std Step Trials= 20
Max Error Tol= 0.3
Flow Tol Ratio= 0.001
Split Flow NTrial= 30
Split Flow Tol= 0.02
Split Flow Ratio= 0.02
Log Output Level= 0
Friction Slope Method= 1
Unsteady Friction Slope Method= 2
Unsteady Bridges Friction Slope Method= 1
Parabolic Critical Depth
Global Vel Dist= 0 , 0 , 0
Global Log Level= 0
CheckData=True
Encroach Param=-1 ,0,0, 0
Mapping Interval=1HOUR
Computation Time Step Use Courant=        0
Computation Time Step Use Time Series=    0
Computation Time Step Count To Double=0
Computation Time Step Max Doubling=0
Computation Time Step Max Halving=0
Computation Time Step Residence Courant=0
Run HTab= 0
Run UNet= 0
Run Sediment= 0
Run PostProcess= 0
Run WQNet= 0
Run RASMapper=-1
UNET Theta= 0
UNET Theta Warmup= 0
UNET ZTol= 0
UNET ZSATol= 0
UNET MxIter= 0
UNET Max Iter WO Improvement= 0
UNET MaxInSteps= 0
UNET DtIC= 0
UNET DtMin= 0
UNET MaxCRTS= 0
UNET WFStab= 0
UNET SFStab= 0
UNET WFX= 1
UNET SFX= 1
UNET Gravity=32.174
UNET 1D Methodology=Finite Difference
UNET DSS MLevel= 1
UNET Pardiso=0
UNET DZMax Abort= 0
UNET Use Existing IB Tables= 0
UNET Froude Reduction=False
UNET Froude Limit= 0
UNET Froude Power= 0
UNET D1 Cores= 0
UNET WindReference=Eulerian
UNET WindDragFormulation=Hsu (1988)
UNET D2 Coriolis=0
UNET D2 Cores= 0
UNET D2 Theta= 1
UNET D2 Theta Warmup= 1
UNET D2 Z Tol= 0.01
UNET D2 Volume Tol= 0.01
UNET D2 Max Iterations= 20
UNET D2 Equation= 0
UNET D2 RampUpFraction=0.1
UNET D2 TimeSlices= 1
UNET D2 Turbulence Formulation=Non-Conservative (original)
UNET D2 Eddy Viscosity=0.3
UNET D2 Transverse Eddy Viscosity=0.1
UNET D2 Smagorinsky Mixing=0
UNET D2 BCVolumeCheck=0
UNET D2 Cores=0
UNET D2 SolverType=PARDISO (Direct)
UNET D2 Minimum Iterations= 2147483647
UNET D2 Maximum Iterations= 2147483647
UNET D2 Restart Number= 10
UNET D2 Relaxation Coeff=1.3
UNET D2 SOR Precondition Iterations= 10
UNET D2 ILUT Maximum Fill= 8
UNET D2 ILUT Tolerance=1E-08
UNET D1D2 MaxIter= 0
UNET D1D2 ZTol=0.01
UNET D1D2 QTol=0.1
UNET D1D2 MinQTol=1
Write IC File= 0
Write IC File at Fixed DateTime=0
Write IC File at Sim End=0
Echo Input=False
Echo Parameters=False
Echo Output=False
Write Detailed= 0
HDF Write Warmup=0
HDF Write Time Slices=0
HDF Flush=0
HDF Compression= 1
HDF Chunk Size= 1
HDF Spatial Parts= 1
HDF Use Max Rows=0
HDF Fixed Rows= 1
Calibration Method= 0
Calibration Iterations= 20
Calibration Max Change=0.05
Calibration Tolerance=0.2
Calibration Maximum=1.5
Calibration Minimum=0.5
Calibration Optimization Method= 1
WQ AD Non Conservative
WQ ULTIMATE=-1
WQ Max Comp Step=1HOUR
WQ Output Interval=15MIN
WQ Output Selected Increments= 0
WQ Output face flow=0
WQ Output face velocity=0
WQ Output face area=0
WQ Output face dispersion=0
WQ Output cell volume=0
WQ Output cell surface area=0
WQ Output cell continuity=0
WQ Output cumulative cell continuity=0
WQ Output face conc=0
WQ Output face dconc_dx=0
WQ Output face courant=0
WQ Output face peclet=0
WQ Output face adv mass=0
WQ Output face disp mass=0
WQ Output cell mass=0
WQ Output cell source sink temp=0
WQ Output nsm pathways=0
WQ Output nsm derived pathways=0
WQ Create Restart=0
WQ Fixed Restart=0
WQ System Summary=0
WQ Write To DSS=0
Sorting and Armoring Iterations= 10
XS Update Threshold= 0.02
Bed Roughness Predictor= 0
Hydraulics Update Threshold= 0.02
Energy Slope Method= 1
Volume Change Method= 1
Sediment Retention Method= 0
Sediment TS Multiplier= 1
Warm Up Method= 0
XS Weighting Method= 0
Number of US Weighted Cross Sections= 1
Number of DS Weighted Cross Sections= 1
Upstream XS Weight=0
Main XS Weight=1
Downstream XS Weight=0
Number of DS XS's Weighted with US Boundary= 1
Upstream Boundary Weight= 1
Weight of XSs Associated with US Boundary= 0
Number of US XS's Weighted with DS Boundary= 1
Downstream Boundary Weight= 0.5
Weight of XSs Associated with DS Boundary= 0.5
Percentile Method= 0
Sediment Output Level= 3
Mass or Volume Output= 0
Output Increment Type= 1
Profile and TS Output Increment= 1
Transport Output Increment 1
XS Output Flag= 0
XS Output Increment= 10
Read HDF5 Sediment Hotstart= 0
Sediment Hotstart Type= 0
Write Gradation File= 0
Read Gradation Hotstart= 0
Write HDF5 File= 1
Write Binary Output= 1
Write DSS Sediment File= 0
DSS Sediment Output Type= 1
SV Curve= 0
Specific Gage Flag= 0
Subcell Erosion Methods= 0
Subcell Deposition Methods= 0
Advection Scheme= 1
Matrix Solver= 0
Implicit Weighting Factor= 1
Maximum Outer Loop Convergence Iterations= 5
Convergence Maximum Absolute= 0.001
Convergence RMSE= 0.0001
Grain Fractions Max Abs Error= 0.001
Max Subgrid Regions= 1
Max Subgrid Length Scale= 3.402823E+38
Initial Layer Thickness= 3.402823E+38
Min Layer Thickness= 3.402823E+38
Max Layer Thickness= 3.402823E+38
Number of Layers= 5

--- SNAKERN.f01 (steady flow) ---

Flow Title=Flow
Program Version=6.20
Number of Profiles= 1
Profile Names=P100yr
River Rch & RM=SNAKERN,Main            ,7719
     324
River Rch & RM=SNAKERN,Main            ,6031
     367
River Rch & RM=SNAKERN,Main            ,4040
     428
River Rch & RM=SNAKERN,Main            ,518
     783
Boundary for River Rch & Prof#=SNAKERN,Main            , 1
Up Type= 0
Dn Type= 1
Dn Known WS=2617.6
DSS Import GetInterval= 0
DSS Import GetPeak= 0
DSS Import FillOption= 0

--- SNAKERN.g01 (geometry) ---

Geom Title=Geometry
Program Version=6.20

River Reach=SNAKERN         ,Main
Reach XY= 30
2226643.64993639 570282.00949122     2226996.368570235.795000017
2227178.62100001570339.2630000112227266.12100002570298.508000001
2227493.72499999570353.975999996     2227778.057570343.235000014
2227895.26100004 570264.179000022228212.93100004570453.915999994
2228371.78500003570460.4259999992228531.04600002570603.167000011
2228793.41599999570610.761999995     2229027.704570728.428000003
2229203.46800002570681.2760000082229422.14700001570723.290000007
2229783.15935896570494.2495167552230029.48199998570467.674999997
     2230620.559570266.7740000042230818.47599998570359.482000008
     2230992.955570310.3510000112231098.59700003570181.922000006
2231453.80600002 570053.363000022231671.25400001570091.903999999
2231899.20500001569918.3799999952232360.86900003569889.182000011
2232471.93700001570010.4710000012232887.43099999570105.914000005
2232999.97500002 570078.093000012233275.57100002570194.937000021
2233302.49300003570266.9430000042233220.72410974570481.707493343

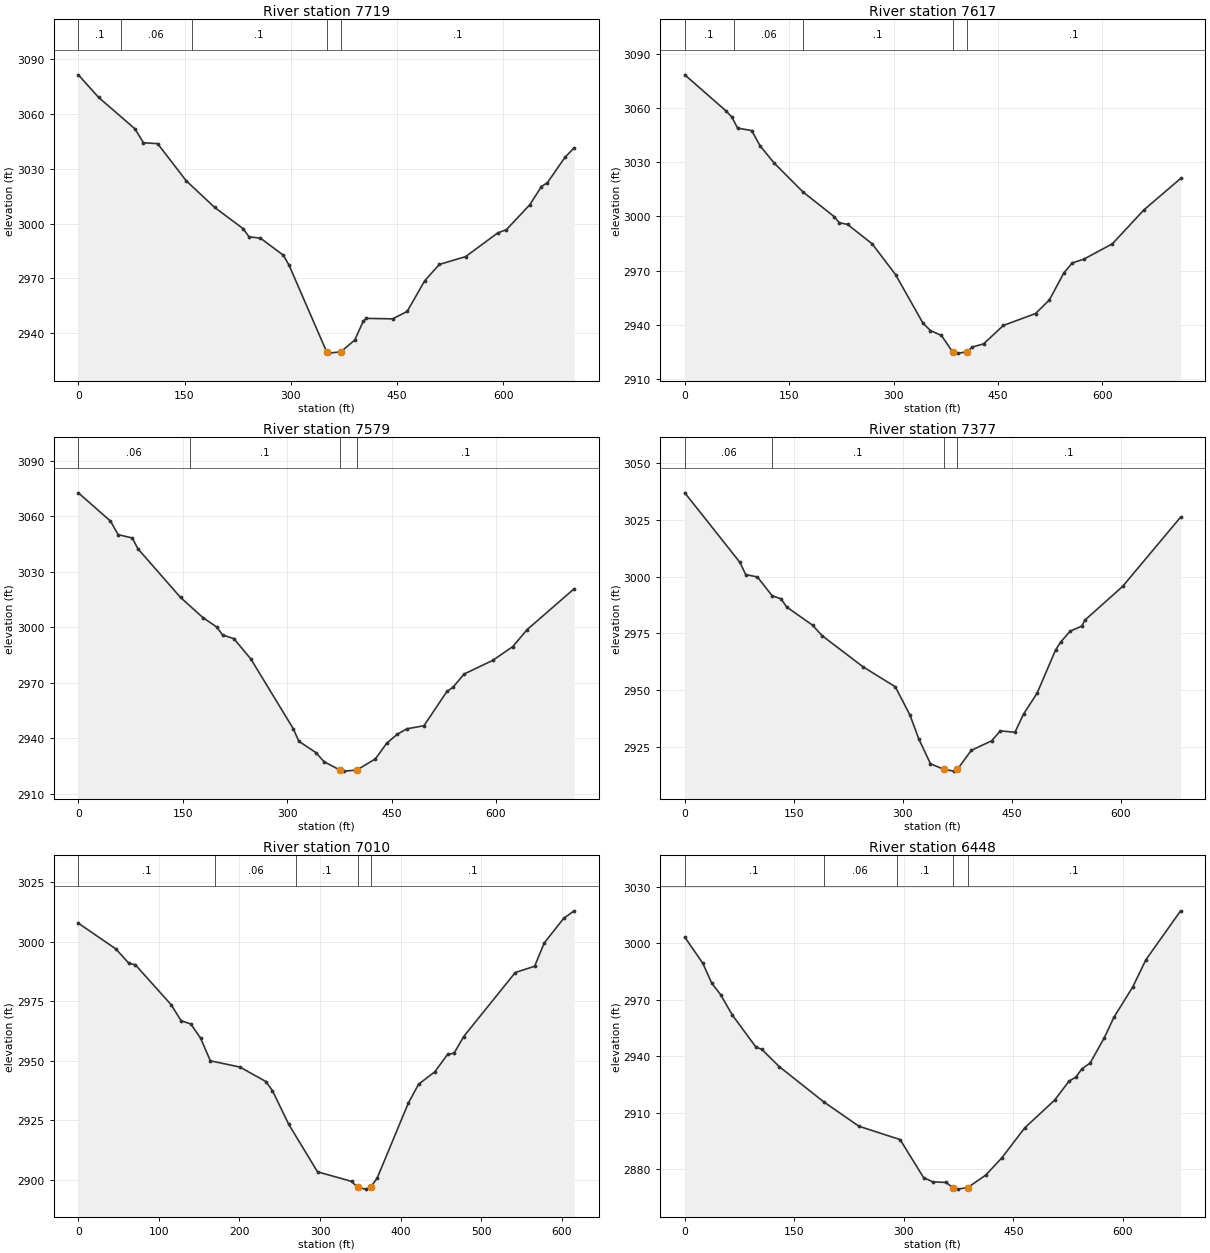
Type RM Length L Ch R = 1 ,7719    ,104.6,101.9,100.8
XS GIS Cut Line= 4
2226600.48657844570640.2745017942226645.67858779570292.992028204
2226638.97654743 570244.337775622226564.89644806569952.523413712
#Sta/Elev= 30
       0 3081.55    28.6  3069.2    79.8 3052.02    91.9 3044.34     112 3043.84
   152.4  3023.5   192.7 3008.85     233  2997.2   241.1 2992.79   257.2 2992.07
   289.5 2982.73   297.6 2977.28  350.76 2929.79   354.1 2929.05  370.81 2929.79
   390.4 2936.21   402.6 2946.61   406.7 2948.09   443.9 2947.83   464.5 2951.89
   489.2 2968.67   509.9 2977.65     547 2981.92   592.4  2994.9   604.8 2996.74
   637.8  3010.4   654.2 3020.35   662.6 3022.43   687.3 3036.29   700.4 3041.57
#Mann= 5 ,-1,0
       0      .1       0      60     .06       0     160      .1       0
  350.76    .045       0  370.81      .1       0
Bank Sta=350.76,370.81
XS Rating Curve= 0 ,0
Exp/Cntr(USF)=0,0
Exp/Cntr=0.3,0.1

Type RM Length L Ch R = 1 ,7617    ,38.4,37.7,36.6
XS GIS Cut Line= 6
2226704.35184696570647.9195953732226763.27629455570299.897076767
2226752.97492683570284.2301746322226743.34413723570260.688244509
 2226735.8535231570216.8146474612226671.34440744569953.959160998
#Sta/Elev= 30
       0 3078.28    59.6  3058.2    67.7 3054.87    75.8 3048.85    96.1 3047.46
   108.3 3038.94   128.5 3029.47   169.6 3013.61   214.6 2999.92   221.9 2996.57
     234 2995.54   269.4 2984.78     303 2967.72   342.2 2940.99     353 2936.89
   368.7 2934.19  384.822925.089   393.1 2924.42  405.422925.089   413.1 2927.79
   429.3 2929.54   457.7 2939.72     504 2946.32   523.8 2953.83   544.4 2968.64
   556.7 2974.28   573.2 2976.34   614.4 2984.88   659.7 3003.63   712.4 3020.98
#Mann= 5 ,-1,0
       0      .1       0      70     .06       0     170      .1       0
  384.82    .045       0  405.42      .1       0
Bank Sta=384.82,405.42
XS Rating Curve= 0 ,0
Exp/Cntr(USF)=0,0
Exp/Cntr=0.3,0.1

Type RM Length L Ch R = 1 ,7579    ,198,202.3,205.2
XS GIS Cut Line= 6
2226739.30804623570637.5754139562226798.23249383570289.552895349
 2226787.9311261570273.885993214 2226778.3003365570250.344063091
2226770.80972237570206.4704660432226706.30060671 569943.61497958
#Sta/Elev= 30
       0 3072.62    46.2 3057.36    57.2 3050.05    77.5 3048.24    85.6 3042.43
   146.8 3016.16   178.9  3005.3   199.2  3000.1   207.3 2995.86   223.5 2993.91
   247.9  2982.9   308.7 2945.37   316.8  2938.5   341.2 2932.43     353 2927.52
  376.032922.911   381.3 2922.38  399.912922.913   426.9 2929.04   443.1 2937.46
   458.2 2942.26   471.9 2945.21   496.6  2946.9   529.6  2965.4   538.2 2967.64
   554.3 2974.79   595.5 2982.19   624.3 2989.65   644.9  2998.8   712.4 3020.84
#Mann= 4 ,-1,0
       0     .06       0     160      .1       0  376.03    .045       0
  399.91      .1       0
Bank Sta=376.03,399.91
XS Rating Curve= 0 ,0
Exp/Cntr(USF)=0,0
Exp/Cntr=0.3,0.1

Type RM Length L Ch R = 1 ,7377    ,363.4,367.3,367.2
XS GIS Cut Line= 3
2226937.40862691570600.2472223462226982.41964637570268.635425865
2226964.37391939569921.407561405
#Sta/Elev= 30
       0 3036.94    75.8 3006.33    83.8 3000.95     100 2999.86   120.2 2991.59
   132.3 2990.27   140.3 2986.62   175.8 2978.65   188.8 2974.05   245.3 2960.29
   289.7  2951.5   309.9    2939     322 2928.52   338.1 2917.57   357.1 2915.07
   370.2 2914.34  375.01 2915.08   394.2 2923.49   422.2 2927.69   434.2 2932.08
   454.3 2931.46   466.3 2939.55   484.8 2948.69   510.3 2967.77   517.6 2971.36
   530.4 2976.01   546.4 2978.25   550.4 2980.81   602.5 2995.72   682.3 3026.24
#Mann= 4 ,-1,0
       0     .06       0     120      .1       0   357.1    .045       0
  375.01      .1       0
Bank Sta=357.1,375.01
XS Rating Curve= 0 ,0
Exp/Cntr(USF)=0,0
Exp/Cntr=0.3,0.1

Type RM Length L Ch R = 1 ,7010    ,570.6,561.9,552.4
XS GIS Cut Line= 4
2227246.12941064570651.0763741892227292.51052229570359.903358964
2227303.81246813570283.1886813992227300.13595791570040.102008002
#Sta/Elev= 30
       0 3007.78    46.5 2996.99    62.7 2990.95    70.8  2990.3   115.3 2973.51
   127.5 2966.84   139.7 2965.43   151.8 2959.45   163.9 2949.97   200.4 2947.37
   232.8 2941.28   240.9 2937.48   261.1 2923.36   296.9 2903.36   339.2 2899.33
  346.632896.846   356.9 2896.08  362.792896.848     371 2900.74   409.5 2932.11
   422.4 2940.15   442.4 2945.33   458.4 2952.67   466.4 2953.16   478.4 2960.18
   542.4 2987.06   566.4 2989.69   578.4 2999.48   602.4 3009.78   615.5 3012.97
#Mann= 5 ,-1,0
       0      .1       0     170     .06       0     270      .1       0
  346.63    .045       0  362.79      .1       0
Bank Sta=346.63,362.79
XS Rating Curve= 0 ,0
Exp/Cntr(USF)=0,0
Exp/Cntr=0.3,0.1

Type RM Length L Ch R = 1 ,6448    ,401.7,416.5,427.6
XS GIS Cut Line= 4
2227803.57021186570665.8279518292227845.58313903570319.965087869
2227805.30786225570278.6245324362227693.27869682570029.904646207
#Sta/Elev= 30
       0 3003.22    24.8 2989.25    36.9 2978.77      49  2972.7    65.1 2961.82
    97.4 2944.79   105.4 2943.62   129.6 2934.35     190 2915.77   238.4 2902.74
   294.8 2895.65     327 2875.42   339.5 2873.21   357.9 2872.87   366.72870.119
   373.4 2869.32  387.33 2870.13   412.1 2876.79     434  2885.9   465.5 2901.89
   506.3 2916.59   526.2 2926.73   535.5 2928.81   543.7 2933.24     555 2936.33
   574.5 2949.84   587.6 2960.67   613.4 2976.79   631.4 2991.25   678.9 3017.21
#Mann= 5 ,-1,0
       0      .1       0     190     .06       0     290      .1       0
   366.7    .045       0  387.33      .1       0
Bank Sta=366.7,387.33
XS Rating Curve= 0 ,0
Exp/Cntr(USF)=0,0
Exp/Cntr=0.3,0.1

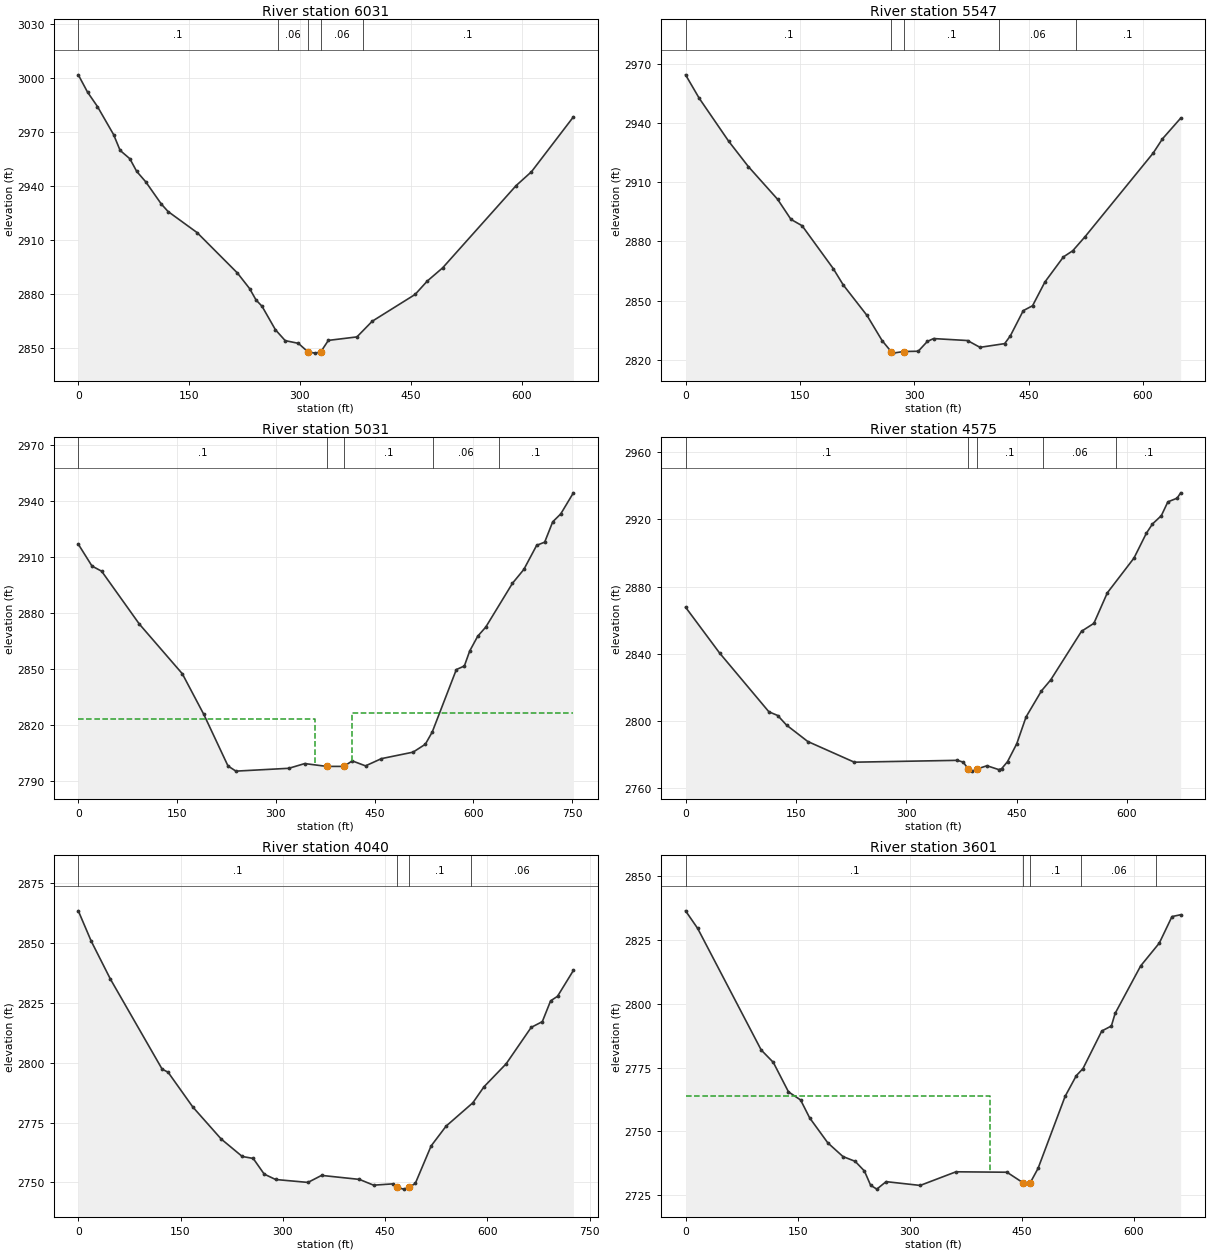
Type RM Length L Ch R = 1 ,6031    ,485,484,480.2
XS GIS Cut Line= 4
2228043.29181845570728.8522502182228161.57546641570464.405157287
2228191.97375871570406.5812348862228274.13569964570102.305616011
#Sta/Elev= 30
       0 3001.57    12.5 2991.97    25.9 2983.98    47.8 2968.37    56.6 2959.62
    69.8 2954.97    79.1 2947.93    91.3 2942.16   112.4 2929.82   121.5 2925.68
   160.9 2913.94   215.4 2891.53   231.9 2882.88   240.6 2876.55   248.7 2873.07
   266.9 2859.99   280.1 2853.98   297.9 2852.48  310.912847.738   320.5 2847.04
  328.212847.739   338.5 2854.11   377.2 2856.05   397.9 2864.75   455.9 2879.61
   472.5  2887.1   493.2 2894.39   592.6 2940.04   613.4 2947.73   670.2 2978.21
#Mann= 5 ,-1,0
       0      .1       0     270     .06       0  310.91    .045       0
  328.21     .06       0  385.02      .1       0
Bank Sta=310.91,328.21
XS Rating Curve= 0 ,0
Exp/Cntr(USF)=0,0
Exp/Cntr=0.3,0.1

Type RM Length L Ch R = 1 ,5547    ,518.8,516,509.1
XS GIS Cut Line= 4
2228457.87215239  570856.57155362228590.37945719570635.285270729
2228603.19226358 570572.747285352228658.61658411570249.590593552
#Sta/Elev= 30
       0 2964.57    17.9 2952.69    56.6 2930.84    82.3 2918.03   120.8 2901.37
   138.3 2891.19   152.9 2887.97   193.7 2866.24   206.9  2857.9   238.1  2842.4
   257.9 2829.64  269.642824.112   272.3 2823.29  286.072824.106   305.3 2824.25
   317.2 2829.21   325.4 2830.68     370 2829.68   386.3 2826.23   418.7 2828.12
   426.2 2832.11   443.1 2844.86   455.3 2847.36   471.5 2859.41   495.8 2872.14
     508 2875.26   524.2 2882.42   613.5 2924.83   625.7 2932.06   649.6 2942.57
#Mann= 5 ,-1,0
       0      .1       0  269.64    .045       0  286.07      .1       0
  411.76     .06       0  511.76      .1       0
Bank Sta=269.64,286.07
XS Rating Curve= 0 ,0
Exp/Cntr(USF)=0,0
Exp/Cntr=0.3,0.1

Type RM Length L Ch R = 1 ,5031    ,454.2,456.4,454.2
XS GIS Cut Line= 4
2229038.42120473571111.9858655382229083.78016348570889.881905808
2229061.56999965570648.8254247622229113.10337815570370.276155861
#Sta/Elev= 30
       0 2917.01    20.8 2905.28    35.5 2902.49    92.7 2874.17     158 2847.51
   190.7 2825.67   227.4 2798.05   239.4 2795.29   319.8 2796.81   343.9 2799.34
  377.522797.822  403.132797.824   416.2 2800.77   436.3 2798.11   460.4 2801.99
   508.5 2805.47   527.1 2809.71   537.6 2816.27   574.2 2849.75   586.4 2851.68
   594.5 2859.72   606.7 2867.65   618.9 2872.54   659.5 2896.05   676.7 2903.44
   696.2 2916.37   708.4  2918.1   720.6 2928.99   732.8 2933.24     752 2944.54
#Mann= 5 ,-1,0
       0      .1       0  377.52    .045       0  403.13      .1       0
  538.77     .06       0  638.77      .1       0
#XS Ineff= 2 , 0
          359.83 2823.44  416.46         2826.55
Permanent Ineff=
       F       F
Bank Sta=377.52,403.13
XS Rating Curve= 0 ,0
Exp/Cntr(USF)=0,0
Exp/Cntr=0.3,0.1

Type RM Length L Ch R = 1 ,4575    ,530.4,534.2,533
XS GIS Cut Line= 4
2229501.39177772571062.3280701672229483.41892514 570706.49031148
 2229478.8409257570626.9851963322229407.75604329570400.571738245
#Sta/Elev= 30
       0 2867.82    46.3 2840.56   113.3 2805.61   125.3  2803.4   137.3 2797.69
   166.2 2787.93   229.4 2775.63   369.6 2776.73   377.6 2775.64  384.46 2771.54
   389.7 2770.31  395.952771.551   409.9 2773.51   425.7 2771.24   429.7 2771.72
   437.8 2775.96   450.4 2786.67     463 2802.57   483.9 2818.03   496.5 2824.58
   538.4 2853.51   555.2 2858.22   573.5 2876.38   609.7 2897.04   626.5 2911.77
   634.9 2917.35   646.9 2922.26   655.8 2930.48   668.4 2932.69   673.2 2935.86
#Mann= 5 ,-1,0
       0      .1       0  384.46    .045       0  395.95      .1       0
  485.93     .06       0  585.93      .1       0
Bank Sta=384.46,395.95
XS Rating Curve= 0 ,0
Exp/Cntr(USF)=0,0
Exp/Cntr=0.3,0.1

Type RM Length L Ch R = 1 ,4040    ,441.3,439.3,437.5
XS GIS Cut Line= 4
2229997.74628939570952.0382520552229965.75738376570677.377093315
2229948.42511293570449.1697198382229905.52821722570232.451781539
#Sta/Elev= 30
       0  2863.4      19 2850.72    47.2 2834.85     123 2797.31   131.7 2796.04
     168 2781.51   209.6 2768.15   240.5 2760.86   256.6 2760.04   272.7 2753.51
   289.4 2751.25   336.9 2750.03   356.9 2752.96   412.4 2751.29   433.2 2748.88
   461.2 2749.42  467.17 2747.96   477.3 2747.23   485.3 2747.97   494.4 2749.62
   517.6 2765.27   539.6 2773.54   578.8 2783.27   595.1 2789.94   627.7 2799.56
   664.4 2814.75   680.7 2817.14   692.9 2825.83     703 2827.72   726.3 2838.52
#Mann= 4 ,-1,0
       0      .1       0  467.17    .045       0   485.3      .1       0
  575.38     .06       0
Bank Sta=467.17,485.3
XS Rating Curve= 0 ,0
Exp/Cntr(USF)=0,0
Exp/Cntr=0.3,0.1

Type RM Length L Ch R = 1 ,3601    ,492.5,492.9,493
XS GIS Cut Line= 4
 2230457.4217684570797.1492177692230422.62162712570577.214861241
2230357.68365069 570339.450423482230290.22713043570158.327979818
#Sta/Elev= 30
       0 2836.38    16.2 2829.49   101.2 2781.86   117.4 2777.01   137.7 2765.46
   153.9 2762.29     166 2755.29   190.3 2745.49   210.6 2740.12   226.9 2738.25
   239.3 2734.46   247.6 2728.87   255.9 2727.36   268.3 2730.29   313.9 2728.81
   361.8 2734.15     430 2733.98  451.68 2729.82  461.032729.786   471.6 2735.48
   507.8  2763.7   522.8 2771.82   531.7 2774.58   556.9 2789.31   569.7 2791.27
   574.7 2796.19   608.9 2814.81   633.8 2823.74   650.8 2834.13   662.4 2834.85
#Mann= 5 ,-1,0
       0      .1       0  451.68    .045       0  461.03      .1       0
  529.14     .06       0  629.14      .1       0
#XS Ineff= 2 , 0
          407.59    2764
Permanent Ineff=
       F       F
Bank Sta=451.68,461.03
XS Rating Curve= 0 ,0
Exp/Cntr(USF)=0,0
Exp/Cntr=0.3,0.1

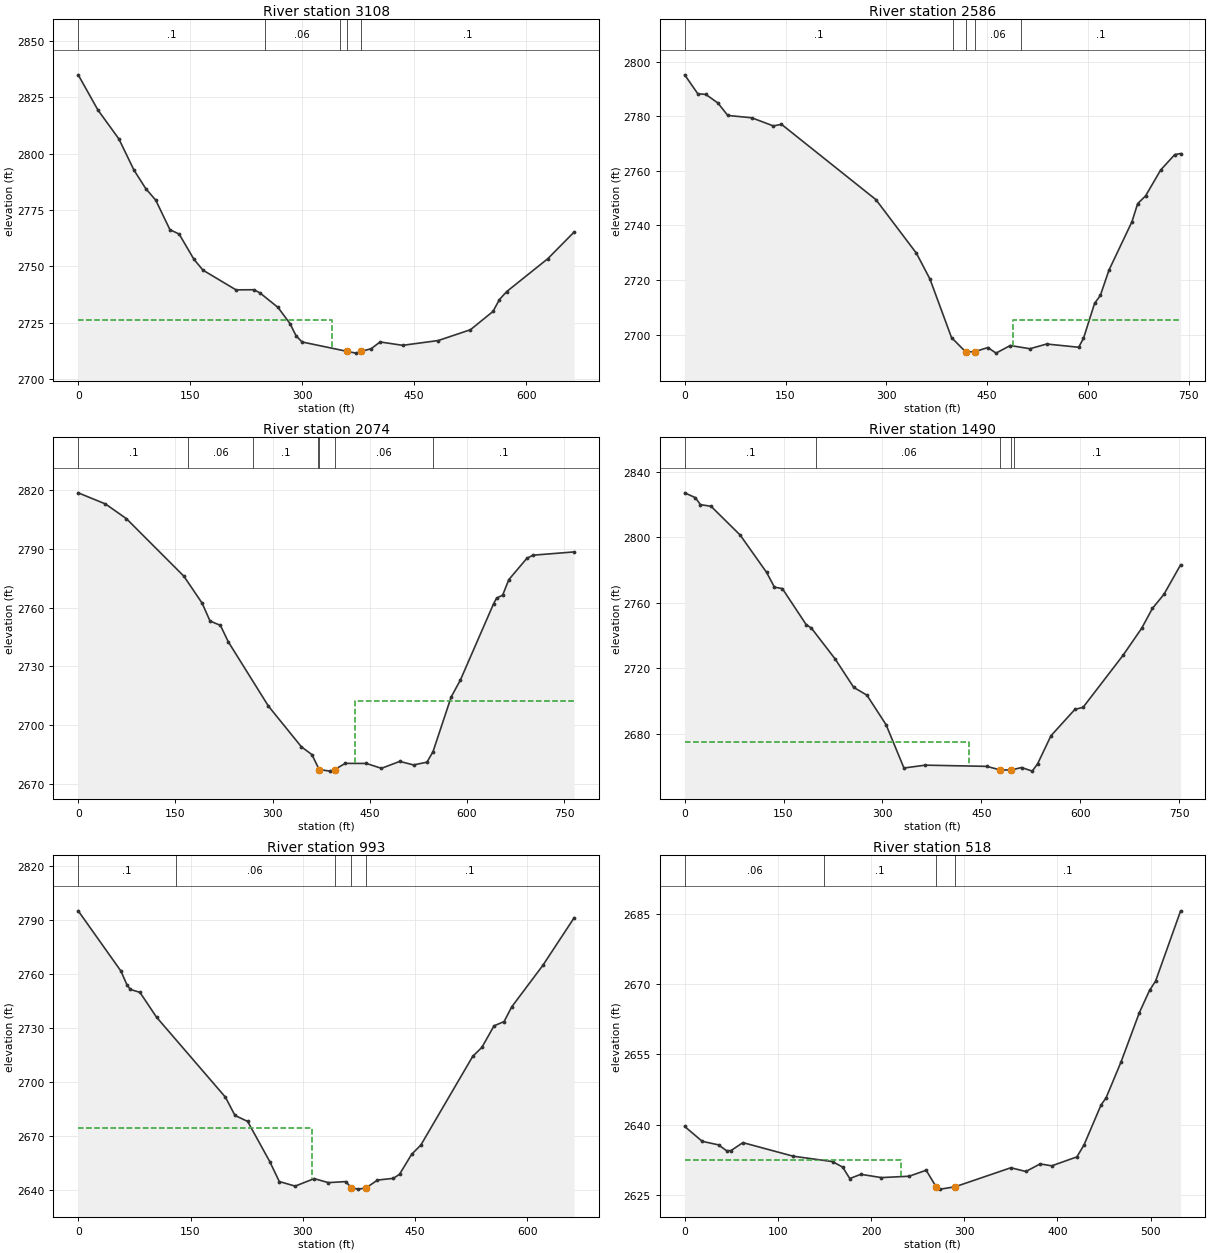
Type RM Length L Ch R = 1 ,3108    ,523.1,522.1,518.4
XS GIS Cut Line= 3
2230849.81417489570727.345390728 2230808.1239189570324.862633399
 2230710.0495852570084.590749139
#Sta/Elev= 30
       0    2835    26.3 2819.45    54.5 2806.55    74.6 2792.78    90.6 2784.46
   103.8 2779.42   122.8 2766.33   135.2 2764.34     155 2753.16   167.1 2748.35
   211.3 2739.61   235.4 2739.66   243.5 2738.24   267.6 2731.81   283.7 2724.61
   291.7 2719.27   299.8 2716.49   359.92712.333   372.1 2711.54  378.89 2712.32
   392.3 2713.49   404.3  2716.5   434.5    2715   482.1 2717.12   525.3 2721.92
   555.5 2730.03   564.1 2735.29   573.9 2738.86     629 2753.46   664.2 2765.28
#Mann= 5 ,-1,0
       0      .1       0     250     .06       0     350      .1       0
   359.9    .045       0  378.89      .1       0
#XS Ineff= 2 , 0
          340.55 2726.37
Permanent Ineff=
       F       F
Bank Sta=359.9,378.89
XS Rating Curve= 0 ,0
Exp/Cntr(USF)=0,0
Exp/Cntr=0.3,0.1

Type RM Length L Ch R = 1 ,2586    ,514.9,512,507.4
XS GIS Cut Line= 4
2231225.94018355570580.567298498 2231261.9432394570182.426782242
2231208.04096659569997.6410831522231156.76097071569861.379196615
#Sta/Elev= 30
       0 2795.16    19.5 2788.24    31.5 2787.97    49.4 2784.85    64.1 2780.28
    99.8 2779.42   131.9 2776.44     144 2777.03   284.5 2749.43   344.8 2729.78
   364.9 2720.33     397 2698.87  418.01 2693.67   431.2 2693.69   451.1 2695.24
   463.2 2693.19   484.4 2695.98   513.6  2694.8   538.6 2696.53   586.1 2695.34
   593.3  2698.6   609.8 2711.41   618.4 2714.34   631.2  2723.6   665.4 2741.34
   673.9 2747.97   685.7 2750.81   708.1 2760.29   729.1 2765.94   737.8 2766.31
#Mann= 5 ,-1,0
       0      .1       0  399.77     .06       0  418.01    .045       0
   431.2     .06       0  499.77      .1       0
#XS Ineff= 2 , 0
                           488.5         2705.37
Permanent Ineff=
       F       F
Bank Sta=418.01,431.2
XS Rating Curve= 0 ,0
Exp/Cntr(USF)=0,0
Exp/Cntr=0.3,0.1

Type RM Length L Ch R = 1 ,2074    ,576.2,584.2,589.4
XS GIS Cut Line= 4
2231781.66002625570450.876675771 2231735.6544984570093.432002482
2231643.84293304569941.4047134062231526.21300562569746.802087218
#Sta/Elev= 30
       0 2818.61    42.1 2812.92    74.3 2805.44     163 2776.07   191.3 2762.24
   203.4 2753.16   219.5 2750.91   231.5  2742.6   293.6 2709.67   344.5  2688.9
   360.7 2684.93  371.882677.286   388.7 2676.49  395.732677.285   412.1 2680.45
   444.7 2680.41     468 2677.92   496.2 2681.45   517.5 2679.66   538.3 2681.07
   547.6 2686.47   575.6 2714.37   589.7 2722.92   641.1    2762   645.7 2764.85
   655.1 2766.38   664.5 2774.25   692.3 2785.12   701.8 2786.76   765.4 2788.44
#Mann= 7 ,-1,0
       0      .1       0     170     .06       0     270      .1       0
  370.39     .06       0  371.88    .045       0  395.73     .06       0
  547.99      .1       0
#XS Ineff= 2 , 0
                          427.44         2712.14
Permanent Ineff=
       F       F
Bank Sta=371.88,395.73
XS Rating Curve= 0 ,0
Exp/Cntr(USF)=0,0
Exp/Cntr=0.3,0.1

Type RM Length L Ch R = 1 ,1490    ,494.7,497,495.6
XS GIS Cut Line= 4
      2232181.23      570389.104 2232202.6771715570060.831991726
2232238.17910858569852.637283414 2232270.7526298569642.847821397
#Sta/Elev= 30
       0 2827.23      16 2824.32      24    2820      40 2819.01    84.1 2801.46
   124.2 2778.66   136.2 2769.59   148.2 2768.69   184.3 2746.72   192.3 2744.53
   228.4 2725.63   256.5 2708.32   276.5 2703.56   305.6  2685.5   332.7 2659.04
   365.1 2660.78   458.5 2660.04   478.8 2657.85  495.572657.845   511.2 2659.34
   527.4 2657.13   535.6 2661.69   555.8 2678.77   592.2 2694.91   604.4 2696.08
   665.1 2727.91   693.4 2744.45   709.6 2756.53   727.2 2765.19   752.5 2783.26
#Mann= 5 ,-1,0
       0      .1       0     200     .06       0   478.8    .045       0
  495.57     .06       0  498.97      .1       0
#XS Ineff= 2 , 0
          431.14 2674.67
Permanent Ineff=
       F       F
Bank Sta=478.8,495.57
XS Rating Curve= 0 ,0
Exp/Cntr(USF)=0,0
Exp/Cntr=0.3,0.1

Type RM Length L Ch R = 1 ,993     ,473,475,473.6
XS GIS Cut Line= 4
2232516.90159943570411.0205637862232619.34712742570115.156146071
2232654.99137827570011.6798519982232701.02487346  569776.1417076
#Sta/Elev= 30
       0 2794.93      57 2761.54    65.4 2753.62    69.7 2751.29    82.4  2749.7
   104.6 2735.92   196.7 2691.48   209.4 2681.36   226.3 2678.07   255.9 2655.74
   268.6 2644.69   289.8 2642.14   315.2 2646.29   334.2 2644.08   357.5 2644.66
  364.892641.183   374.4 2640.47  384.642641.181   399.8  2645.5     421 2646.45
   429.2  2648.7   445.5 2659.85   457.7 2664.92     527 2714.16   539.2 2719.13
   555.5 2731.11   568.9 2733.47   579.1 2741.63   620.7 2764.68   662.5 2791.09
#Mann= 5 ,-1,0
       0      .1       0     130     .06       0   343.1      .1       0
  364.89    .045       0  384.64      .1       0
#XS Ineff= 2 , 0
          312.85 2674.21
Permanent Ineff=
       F       F
Bank Sta=364.89,384.64
XS Rating Curve= 0 ,0
Exp/Cntr(USF)=0,0
Exp/Cntr=0.3,0.1

Type RM Length L Ch R = 1 ,518     ,105.1,106.1,105.6
XS GIS Cut Line= 4
2232842.94686185570249.4712291252233081.00902744570144.751905821
  2233098.841346570099.7758890832232926.52756128569956.961683939
#Sta/Elev= 30
       0 2639.61    18.8 2636.44    36.3 2635.68      45 2634.43    49.7 2634.46
    62.5 2636.16   116.5 2633.26   158.7 2632.11   169.6 2630.93   177.2  2628.5
   189.1  2629.4   211.1  2628.7   240.9 2628.99   259.2 2630.27   269.82626.762
   274.5 2626.24290.25142626.741   350.1  2630.8   366.2    2630   381.5 2631.62
     394 2631.21     421 2633.12   428.7 2635.71     447 2644.24   452.2 2645.67
   468.4  2653.4     488 2663.88     499 2668.66   505.4  2670.6   532.3  2685.6
#Mann= 4 ,-1,0
       0     .06       0     150      .1       0   269.8    .045       0
290.2514      .1       0
#XS Ineff= 2 , 0
           231.9 2632.46
Permanent Ineff=
       F       F
Bank Sta=269.8,290.2514
XS Rating Curve= 0 ,0
Exp/Cntr(USF)=0,0
Exp/Cntr=0.3,0.1

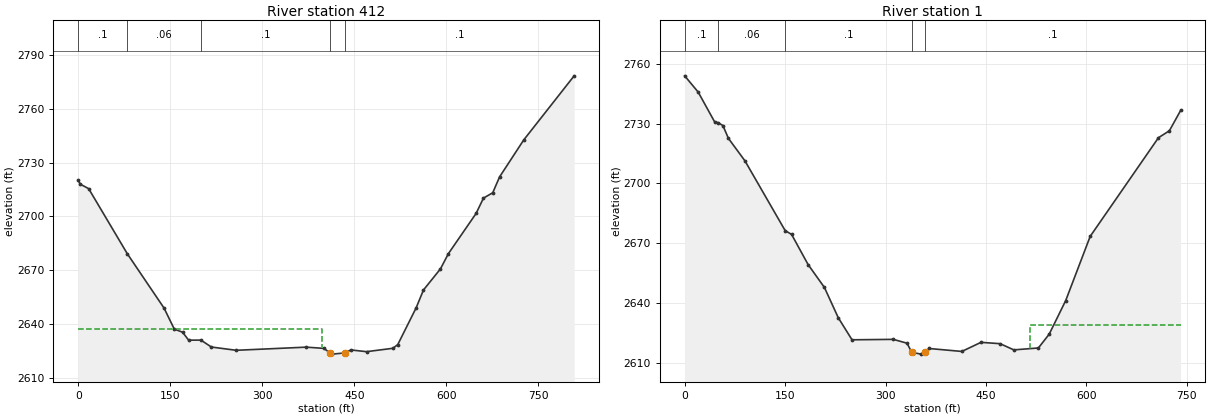
Type RM Length L Ch R = 1 ,412     ,387.5,410.6,422.4
XS GIS Cut Line= 4
2232861.64193001570418.4054243292233178.14433285 570184.01834772
2233232.96559084570045.2662094842233475.19598759569936.940442549
#Sta/Elev= 30
       0 2720.24     3.2 2717.98      17 2715.46      802679.145     140 2648.78
   156.6  2637.1   170.1 2635.37     180 2630.93     200 2630.96   217.1  2627.1
   257.5 2625.28   371.6 2627.03   400.7 2626.35   409.9 2623.88   414.1 2623.14
   435.6 2623.84   444.2 2625.49     470 2624.51     513  2626.4   520.9 2628.48
   550.9    2649   562.8 2658.93   590.4 2670.66   603.5 2679.24   648.5 2701.59
   660.6 2710.19   675.7 2713.16   686.8 2721.99   726.2 2742.62   808.4 2778.39
#Mann= 5 ,-1,0
       0      .1       0      80     .06       0     200      .1       0
   409.9    .045       0   435.6      .1       0
#XS Ineff= 2 , 0
          396.68 2637.19
Permanent Ineff=
       F       F
Bank Sta=409.9,435.6
XS Rating Curve= 0 ,0
Exp/Cntr=0.3,0.1

Type RM Length L Ch R = 1 ,1       ,361.5,362.9,364.3
XS GIS Cut Line= 4
2232880.46831732 570539.779918382233180.27179959570471.489188105
2233322.78313178570502.8587228482233604.59620075570447.666147604
#Sta/Elev= 30
       0 2753.97    20.2 2745.79    44.8 2730.81      50 2730.45    57.1 2729.01
    65.3 2722.59      90  2711.3     1502676.317   159.7 2674.35   184.3 2659.24
   208.7 2647.74   229.4 2632.53   249.9 2621.48   311.5  2621.7     332 2619.78
     339 2615.26   352.6 2614.29  358.29 2615.27   364.7 2617.12   413.9 2615.64
   442.5 2620.21   471.1 2619.53   491.5 2616.42   528.2 2617.38   544.3 2624.29
     569 2641.17   605.6 2673.42   707.5 2722.91   723.8 2726.39   740.6 2736.57
#Mann= 5 ,-1,0
       0      .1       0      50     .06       0     150      .1       0
     339    .045       0  358.29      .1       0
#XS Ineff= 2 , 0
                          515.87          2628.7
Permanent Ineff=
       F       F
Bank Sta=339,358.29
XS Rating Curve= 0 ,0
Exp/Cntr=0.3,0.1
LCMann Table=0

Chan Stop Cuts=-1
Use User Specified Reach Order=0
Composite Channel Slope=5